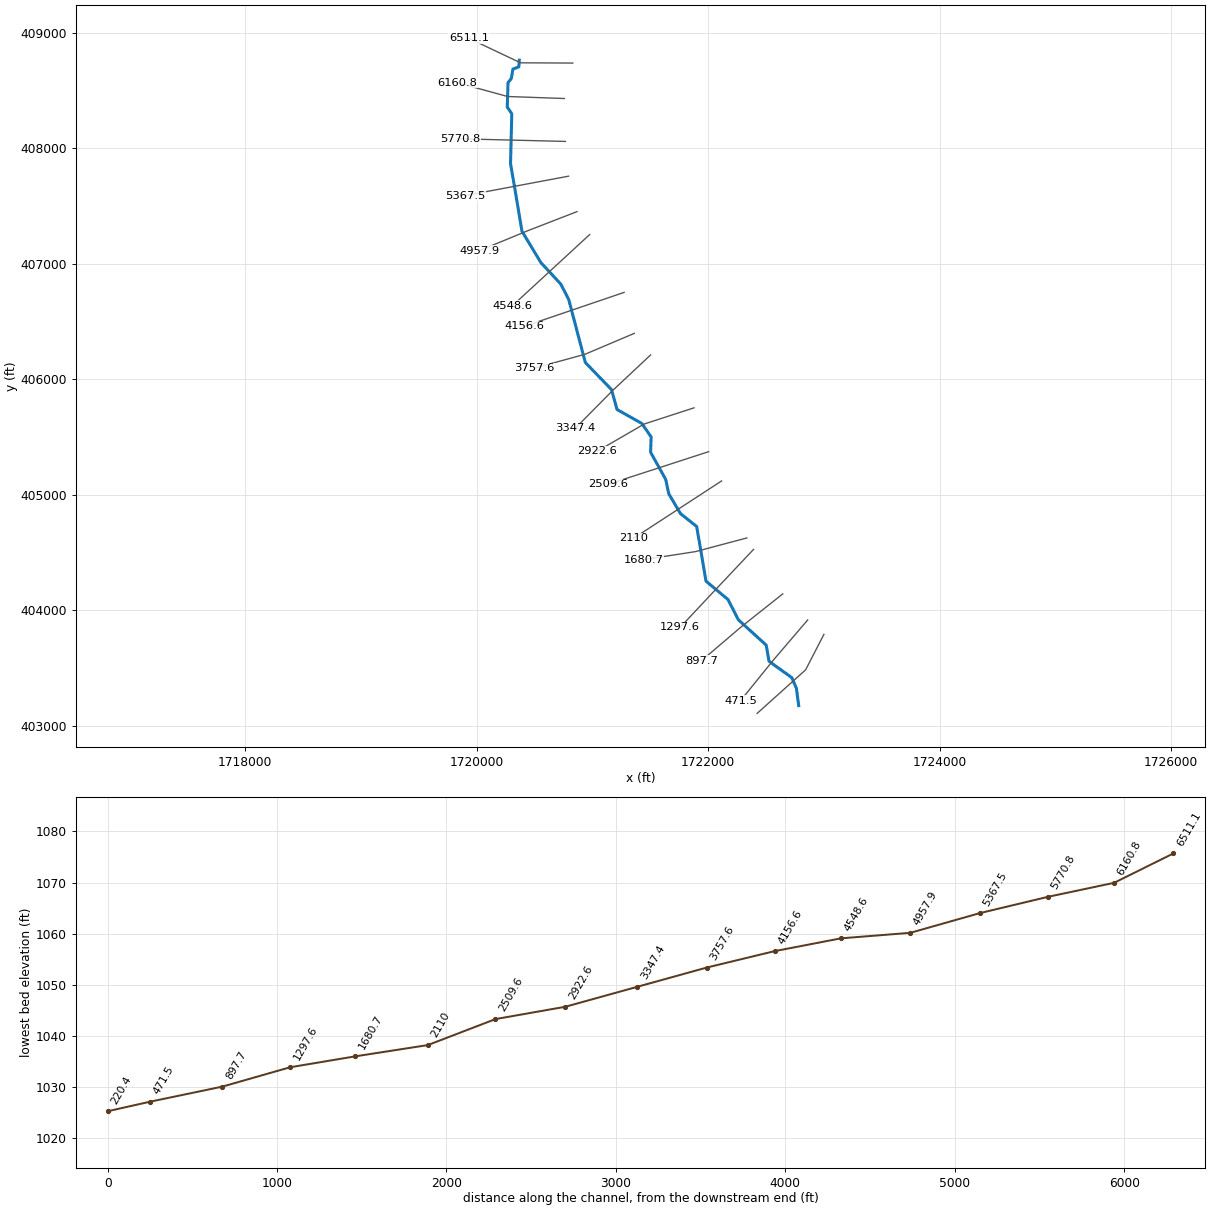
--- LFCmbllRn.prj (project) ---

Proj Title=LFCmbllRn
Current Plan=p01
Default Exp/Contr=0,0
English Units
Geom File=g01
Flow File=f01
Plan File=p01
BEGIN DESCRIPTION:
END DESCRIPTION:
DSS Export Rating Curves= 0
DSS Export Rating Curve Sorted= 0
DSS Export Volume Flow Curves= 0
DXF OffsetX= 0
DXF OffsetY= 0
DXF ScaleX= 0
DXF ScaleY= 0

--- LFCmbllRn.p01 (plan) ---

Plan Title=Floodplain
Program Version=4.00
Geom File=g01
Flow File=f01
K Sum by GR=0
Std Step Tol=0.01
Critical Tol=0.01
Num of Std Step Trials=20
Max Error Tol=0.3
Flow Tol Ratio=0.001
Split Flow NTrial=30
Split Flow Tol=0.02
Split Flow Ratio=0.02
Log Output Level=0
Friction Slope Method=1
Unsteady Friction Slope Method=2
Unsteady Bridges Friction Slope Method=1
Global Log Level=0
CheckData=False
Run HTab=0
Run UNet=0
Run PostProcess=0
UNET Theta=0
UNET Theta Warmup=0
UNET ZTol=0
UNET ZSATol=0
UNET MxIter=0
UNET MaxInSteps=0
UNET DtIC=0
UNET DtMin=0
UNET MaxCRTS=0
UNET WFStab=0
UNET SFStab=0
UNET WFX=0
UNET SFX=0
UNET DSS MLevel=0
UNET DZMax Abort=0
UNET Convert EG Bridges=0
UNET Use Existing IB Tables=0
UNET Froude Limit=0
UNET Froude Power=0
Write IC File=0
Echo Input=False
Echo Output=False
Write Detailed=0

--- LFCmbllRn.f01 (steady flow) ---

Flow Title=NFF Regression Equation
Program Version=4.00
Number of Profiles= 1
Profile Names=P100yr
River Rch & RM=LFCmbllRn,Main            ,6511.1
828.2421
River Rch & RM=LFCmbllRn,Main            ,3757.6
 918.619
River Rch & RM=LFCmbllRn,Main            ,3347.4
1020.309
River Rch & RM=LFCmbllRn,Main            ,220.4
 1023.69
Boundary for River Rch & Prof#=LFCmbllRn,Main            , 1
Up Type= 0
Dn Type= 3
Dn Slope=0.008037
DSS Import GetInterval= 0
DSS Import GetPeak= 0
DSS Import FillOption= 0

--- LFCmbllRn.g01 (geometry) ---

Geom Title=USGS 3m DEM
Program Version=4.00

River Reach=LFCmbllRn     ,Main
Reach XY= 30
     1720368.307      408762.422     1720364.717      408704.977
     1720312.987      408684.785     1720300.091      408604.449
     1720271.369      408568.546     1720264.677      408355.399
     1720303.682      408299.273     1720292.911      407868.437
     1720392.040      407280.866     1720555.003      407010.354
     1720727.338      406823.658     1720795.553      406690.817
     1720939.165      406145.091     1721165.001      405910.618
     1721213.311      405737.873     1721427.447      405617.316
     1721507.563      405500.715     1721503.171      405367.496
     1721633.462      405133.266     1721659.813      405008.831
     1721760.825      404837.550     1721901.363      404724.826
     1721981.880      404251.973     1722172.192      404092.404
     1722261.854      403916.898     1722501.578      403698.604
     1722526.465      403558.065     1722723.546      403416.461
     1722763.040      403323.113     1722782.462      403174.562

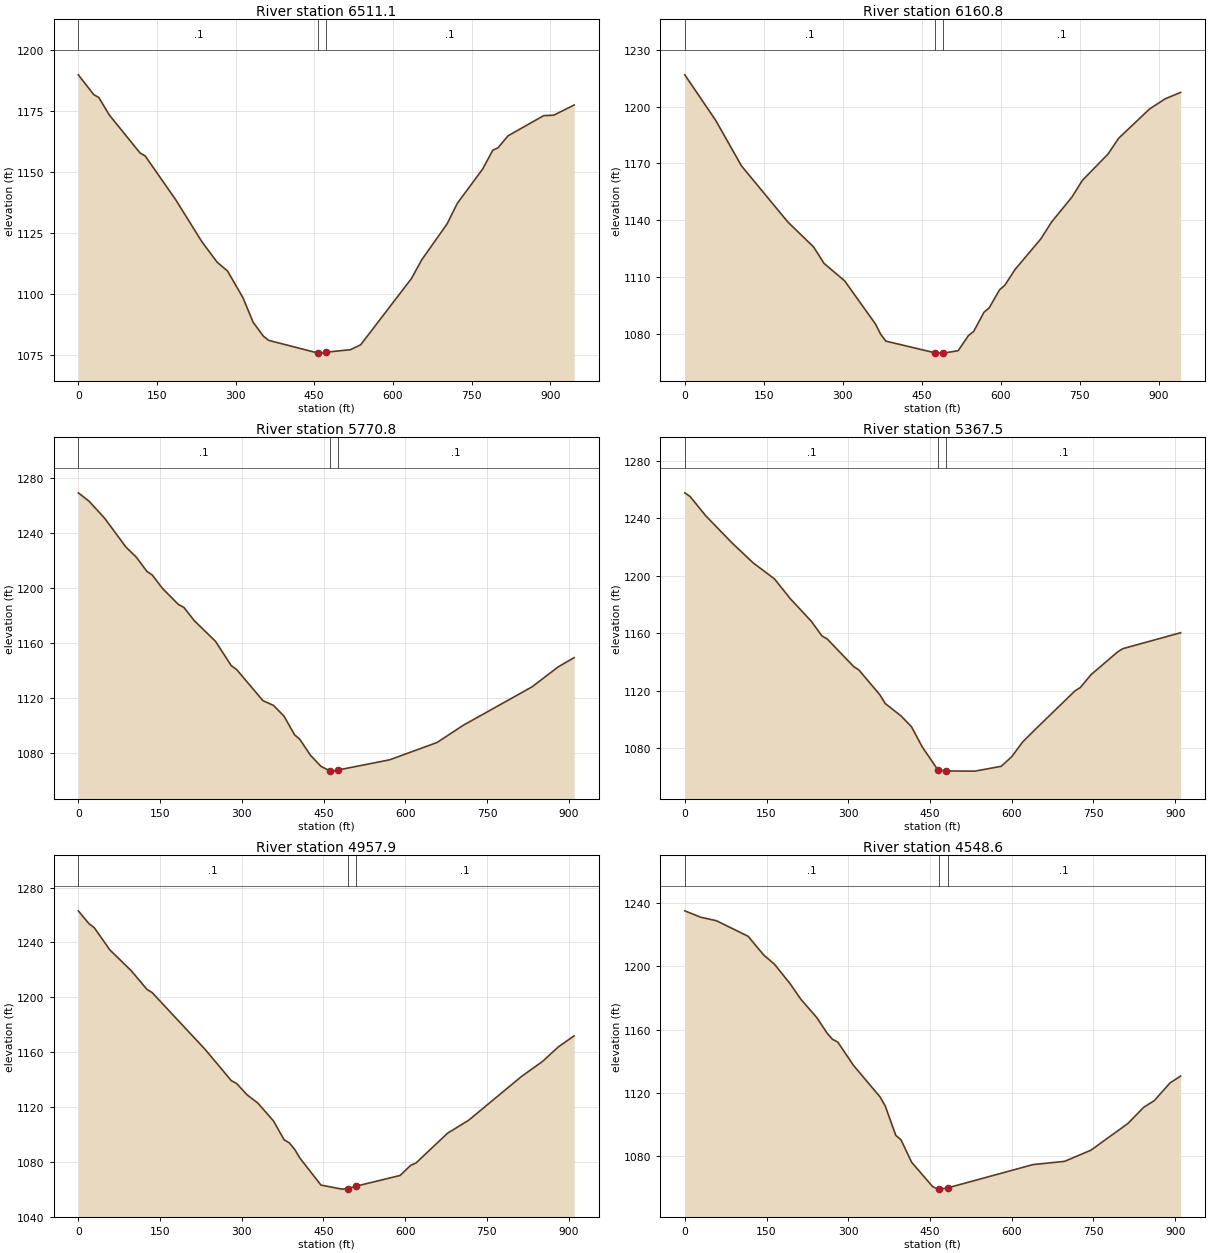
Type RM Length L Ch R = 1 ,6511.1,346.748,350.303,353.397
XS GIS Cut Line= 3
     1720830.888      408737.582     1720379.613      408739.723
     1719932.792      408951.646
#Sta/Elev= 30
       0 1189.81    29.4 1181.70    39.2 1180.49    58.9 1173.40   117.7 1157.77
   127.5 1156.57   186.4 1138.38   235.5 1121.44   264.9 1112.95   284.5 1109.40
   313.9 1098.48   333.6 1088.28   353.2 1082.61   363.0 1080.94   457.5 1075.71
   461.0 1075.70   472.5 1076.08   519.2 1077.11   538.6 1079.13   635.5 1106.30
   654.9 1113.92   703.4 1128.68   722.8 1137.07   771.3 1151.21   790.7 1158.94
   800.4 1159.86   819.8 1164.82   887.6 1173.07   907.0 1173.27   945.8 1177.44
#Mann= 3 , 0 , 0
       0     0.1       0   457.5   0.045       0   472.5     0.1       0
Bank Sta=   457.5,   472.5
Exp/Cntr=0.3,0.1

Type RM Length L Ch R = 1 ,6160.8,389.723,389.999,394.086
XS GIS Cut Line= 3
     1720757.082      408430.691     1720267.748      408448.034
     1719831.803      408567.797
#Sta/Elev= 30
       0 1216.76    58.8 1192.69   107.7 1168.71   195.9 1139.07   244.8 1125.90
   264.4 1117.30   303.6 1108.07   362.3 1085.24   372.1 1079.85   381.9 1076.27
   475.9 1070.07   489.6 1069.94   490.9 1069.94   519.1 1071.21   538.8 1079.23
   548.6 1081.35   568.3 1091.53   578.1 1093.81   597.8 1103.34   607.6 1105.67
   627.2 1114.06   676.4 1130.27   696.0 1138.88   735.3 1152.29   755.0 1161.03
   804.1 1175.06   823.8 1183.24   882.8 1198.77   912.3 1204.11   941.7 1207.47
#Mann= 3 , 0 , 0
       0     0.1       0   475.9   0.045       0   490.9     0.1       0
Bank Sta=   475.9,   490.9
Exp/Cntr=0.3,0.1

Type RM Length L Ch R = 1 ,5770.8,398.531,403.295,408.059
XS GIS Cut Line= 3
     1720767.128      408059.055     1720312.271      408070.426
     1719857.413      408081.797
#Sta/Elev= 30
       0 1269.13    19.4 1263.16    48.4 1250.65    87.1 1229.90   106.5 1222.42
   125.9 1212.11   135.5 1209.58   154.9 1199.57   183.9 1188.03   193.6 1186.05
   213.0 1176.29   251.7 1161.42   280.7 1143.72   290.4 1140.99   338.8 1118.34
   358.2 1114.90   377.6 1107.05   396.9 1093.55   406.6 1090.27   426.0 1078.74
   445.3 1070.67   461.8 1067.37   464.7 1067.20   476.8 1068.03   571.2 1075.39
   658.3 1087.96   706.7 1100.52   832.6 1128.32   881.0 1142.93   910.0 1149.54
#Mann= 3 , 0 , 0
       0     0.1       0   461.8   0.045       0   476.8     0.1       0
Bank Sta=   461.8,   476.8
Exp/Cntr=0.3,0.1

Type RM Length L Ch R = 1 ,5367.5,404.867,409.608,414.349
XS GIS Cut Line= 3
     1720793.739      407758.243     1720346.583      407674.125
     1719899.426      407590.006
#Sta/Elev= 30
       0 1257.74     9.7 1255.21    38.7 1241.65    87.1 1222.72   125.9 1208.84
   164.6 1197.83   193.6 1184.05   232.3 1168.28   251.7 1158.12   261.4 1156.00
   309.8 1136.86   319.5 1134.44   358.2 1117.06   367.9 1111.04   396.9 1102.43
   416.3 1094.77   435.6 1080.97   464.3 1064.98   479.3 1064.11   532.4 1064.00
   580.9 1067.37   600.2 1074.12   619.6 1084.11   648.6 1095.03   716.4 1119.97
   726.1 1122.24   745.4 1131.10   793.8 1146.82   803.5 1149.21   910.0 1160.34
#Mann= 3 , 0 , 0
       0     0.1       0   464.3   0.045       0   479.3     0.1       0
Bank Sta=   464.3,   479.3
Exp/Cntr=0.3,0.1

Type RM Length L Ch R = 1 ,4957.9,401.321,409.345,417.37
XS GIS Cut Line= 3
     1720867.418      407451.420     1720443.186      407286.603
     1720022.667      407112.911
#Sta/Elev= 30
       0 1263.02    19.4 1253.69    29.1 1250.79    58.1 1234.44    96.8 1219.51
   125.9 1205.78   135.6 1203.37   232.4 1162.17   280.8 1139.23   290.5 1137.17
   309.9 1128.85   329.2 1123.01   358.3 1109.83   377.7 1096.14   387.3 1093.85
   397.0 1089.20   406.7 1082.78   445.4 1063.08   484.2 1060.15   494.6 1060.58
   509.6 1062.30   590.6 1070.10   610.0 1077.49   619.7 1079.18   677.8 1100.94
   716.5 1110.38   813.3 1142.24   852.0 1153.21   881.1 1163.85   910.1 1171.91
#Mann= 3 , 0 , 0
       0     0.1       0   494.6   0.045       0   509.6     0.1       0
Bank Sta=   494.6,   509.6
Exp/Cntr=0.3,0.1

Type RM Length L Ch R = 1 ,4548.6,401.428,392.005,382.582
XS GIS Cut Line= 3
     1720976.964      407253.079     1720642.628      406944.461
     1720308.293      406635.844
#Sta/Elev= 30
       0 1235.13    29.0 1231.10    58.1 1228.87   116.2 1219.03   145.2 1207.05
   164.6 1201.34   193.6 1188.86   213.0 1179.20   242.0 1167.71   261.4 1157.63
   271.1 1153.84   280.7 1152.14   309.8 1137.27   358.2 1117.50   367.9 1111.66
   387.2 1093.12   396.9 1090.21   416.3 1076.09   455.0 1060.62   464.7 1059.07
   467.2 1059.09   482.2 1059.83   638.9 1074.58   697.0 1076.64   745.4 1083.71
   813.2 1100.59   842.2 1110.83   861.6 1115.04   890.6 1126.27   910.0 1130.57
#Mann= 3 , 0 , 0
       0     0.1       0   467.2   0.045       0   482.2     0.1       0
Bank Sta=   467.2,   482.2
Exp/Cntr=0.3,0.1

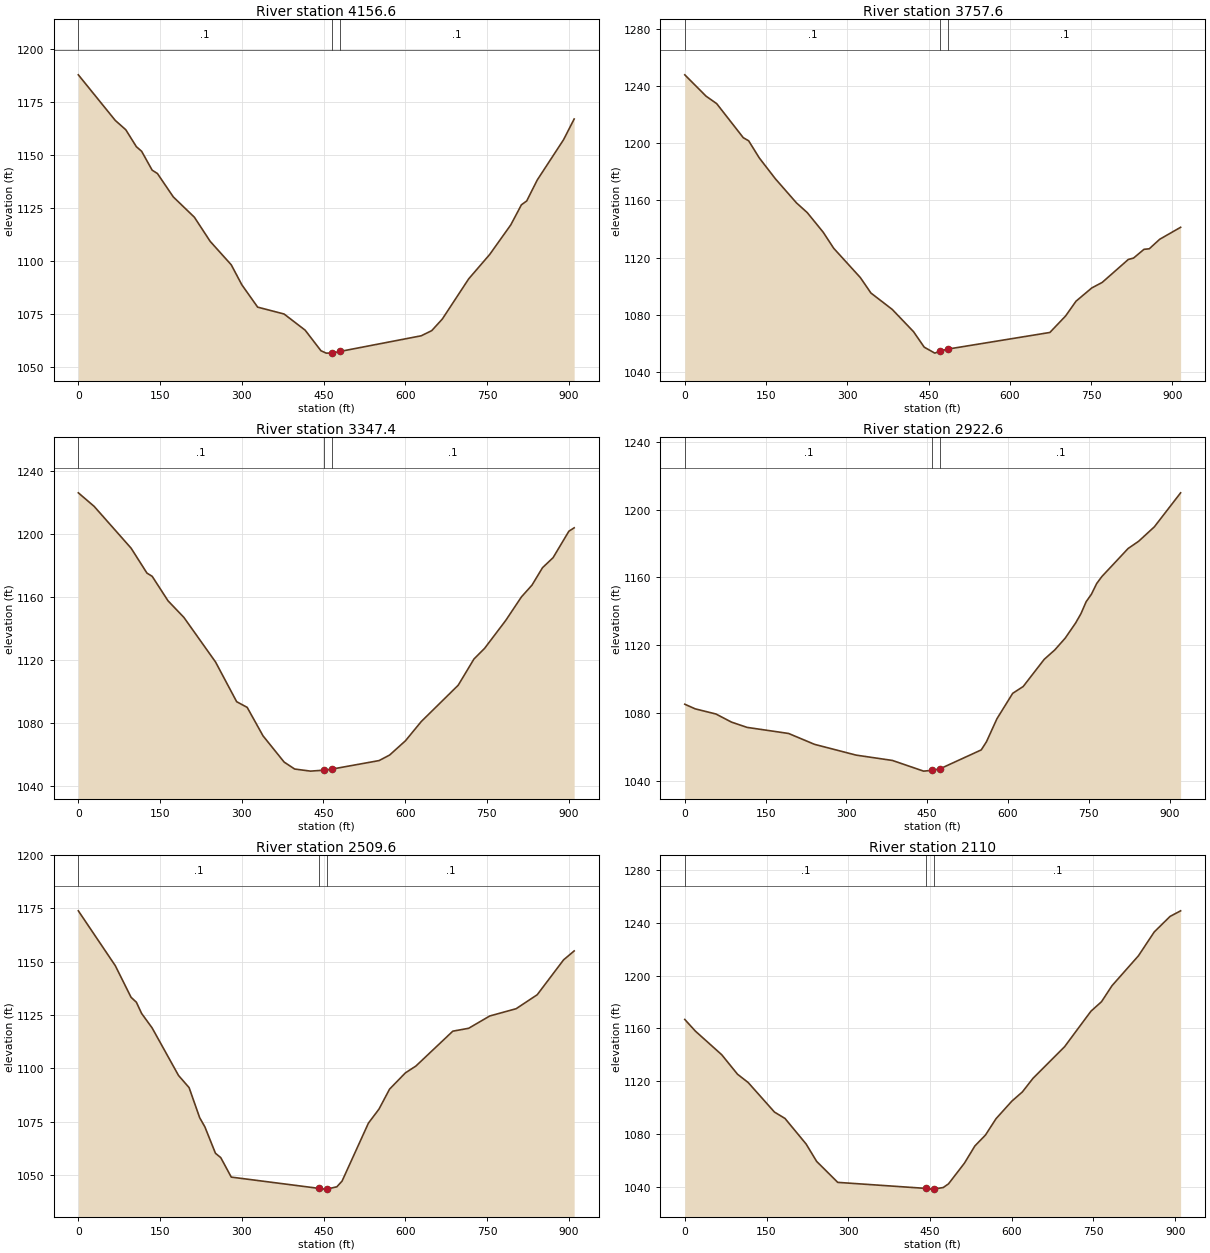
Type RM Length L Ch R = 1 ,4156.6,399.627,398.939,397.599
XS GIS Cut Line= 3
     1721274.476      406752.186     1720843.814      406605.369
     1720413.152      406458.553
#Sta/Elev= 30
       0 1187.74    67.8 1166.25    87.1 1161.85   106.5 1153.87   116.2 1151.69
   135.5 1142.80   145.2 1141.21   174.3 1130.19   213.0 1120.62   242.0 1109.24
   280.7 1098.18   300.1 1088.77   329.1 1078.24   377.6 1075.00   416.3 1067.38
   445.3 1057.68   455.0 1056.56   465.6 1056.62   480.6 1057.37   629.3 1064.73
   648.6 1067.16   668.0 1072.61   716.4 1091.55   755.1 1103.10   793.8 1117.06
   813.2 1126.48   822.9 1128.28   842.2 1138.14   890.6 1157.18   910.0 1166.92
#Mann= 3 , 0 , 0
       0     0.1       0   465.6   0.045       0   480.6     0.1       0
Bank Sta=   465.6,   480.6
Exp/Cntr=0.3,0.1

Type RM Length L Ch R = 1 ,3757.6,399.07,410.257,423.069
XS GIS Cut Line= 3
     1721362.453      406397.482     1720937.615      406216.954
     1720500.122      406096.266
#Sta/Elev= 30
       0 1247.74    39.3 1232.82    58.9 1227.61   108.0 1203.81   117.9 1201.67
   137.5 1189.71   167.0 1175.23   206.2 1158.28   225.9 1151.58   255.4 1137.87
   275.0 1126.55   324.1 1106.13   343.7 1095.32   383.0 1083.88   422.3 1068.34
   442.0 1057.54   461.6 1053.36   471.7 1054.83   486.7 1056.24   674.0 1067.79
   703.0 1079.29   722.3 1089.64   751.3 1098.87   770.6 1102.74   818.9 1118.81
   828.5 1119.76   847.8 1125.87   857.5 1126.23   876.8 1132.89   915.4 1141.25
#Mann= 3 , 0 , 0
       0     0.1       0   471.7   0.045       0   486.7     0.1       0
Bank Sta=   471.7,   486.7
Exp/Cntr=0.3,0.1

Type RM Length L Ch R = 1 ,3347.4,431.98,424.76,418.385
XS GIS Cut Line= 3
     1721502.698      406210.230     1721170.875      405898.355
     1720851.193      405574.677
#Sta/Elev= 30
       0 1226.27    29.1 1217.65    96.9 1191.12   126.0 1175.30   135.6 1173.26
   164.7 1157.71   193.8 1147.18   251.9 1118.88   290.7 1093.66   310.0 1090.06
   339.1 1071.98   377.9 1055.31   397.2 1050.92   426.3 1049.59   450.6 1050.19
   465.6 1050.87   552.2 1056.29   571.5 1059.80   600.6 1068.86   629.6 1081.07
   697.4 1104.12   726.4 1120.79   745.8 1127.50   784.5 1145.17   813.5 1160.19
   832.9 1167.68   852.2 1178.73   871.6 1185.10   900.6 1201.89   910.3 1204.05
#Mann= 3 , 0 , 0
       0     0.1       0   450.6   0.045       0   465.6     0.1       0
Bank Sta=   450.6,   465.6
Exp/Cntr=0.3,0.1

Type RM Length L Ch R = 1 ,2922.6,416.208,413.033,408.041
XS GIS Cut Line= 3
     1721878.455      405752.784     1721447.909      405612.606
     1721043.511      405378.001
#Sta/Elev= 30
       0 1085.16    19.3 1082.43    57.8 1079.39    86.7 1074.60   115.6 1071.49
   192.7 1067.90   240.8 1061.48   317.9 1055.13   385.4 1051.98   443.2 1045.68
   459.5 1046.13   474.5 1047.17   550.2 1058.20   559.9 1062.99   579.4 1076.61
   608.6 1091.58   628.1 1095.62   667.1 1111.64   686.6 1117.16   706.0 1124.12
   725.5 1133.14   735.3 1138.59   745.0 1145.68   754.7 1150.04   764.5 1156.38
   774.2 1160.53   822.9 1177.06   842.4 1181.32   871.6 1189.85   920.3 1209.90
#Mann= 3 , 0 , 0
       0     0.1       0   459.5   0.045       0   474.5     0.1       0
Bank Sta=   459.5,   474.5
Exp/Cntr=0.3,0.1

Type RM Length L Ch R = 1 ,2509.6,393.529,399.533,405.537
XS GIS Cut Line= 3
     1722004.390      405373.119     1721571.744      405232.258
     1721139.097      405091.396
#Sta/Elev= 30
       0 1173.89    67.8 1148.16    96.8 1133.30   106.5 1131.00   116.2 1125.70
   135.5 1118.90   183.9 1096.61   203.3 1090.90   222.7 1076.80   232.3 1072.46
   251.7 1060.08   261.4 1058.05   280.7 1048.90   441.6 1043.61   455.0 1043.26
   456.6 1043.30   474.4 1044.35   484.0 1047.01   532.4 1074.23   551.8 1080.82
   571.2 1090.19   600.2 1097.81   619.6 1101.05   687.3 1117.40   716.4 1118.76
   755.1 1124.53   803.5 1127.94   842.2 1134.50   890.6 1150.88   910.0 1155.06
#Mann= 3 , 0 , 0
       0     0.1       0   441.6   0.045       0   456.6     0.1       0
Bank Sta=   441.6,   456.6
Exp/Cntr=0.3,0.1

Type RM Length L Ch R = 1 ,2110,436.973,429.324,421.674
XS GIS Cut Line= 3
     1722116.712      405119.939     1721735.753      404871.150
     1721354.795      404622.361
#Sta/Elev= 30
       0 1166.69    19.4 1157.89    67.8 1139.97    96.8 1125.19   116.2 1118.98
   164.6 1096.54   183.9 1091.71   222.7 1072.33   242.0 1059.17   280.7 1043.29
     443 1038.70   455.0 1038.17     458 1038.25   474.4 1039.40   484.0 1042.17
   513.1 1057.77   532.4 1070.88   551.8 1079.12   571.2 1091.52   600.2 1104.81
   619.6 1111.82   638.9 1122.03   697.0 1146.03   745.4 1172.95   764.8 1180.14
   784.1 1192.30   832.6 1214.95   861.6 1233.01   890.6 1244.76   910.0 1249.00
#Mann= 3 , 0 , 0
       0     0.1       0     443   0.045       0     458     0.1       0
Bank Sta=     443,     458
Exp/Cntr=0.3,0.1

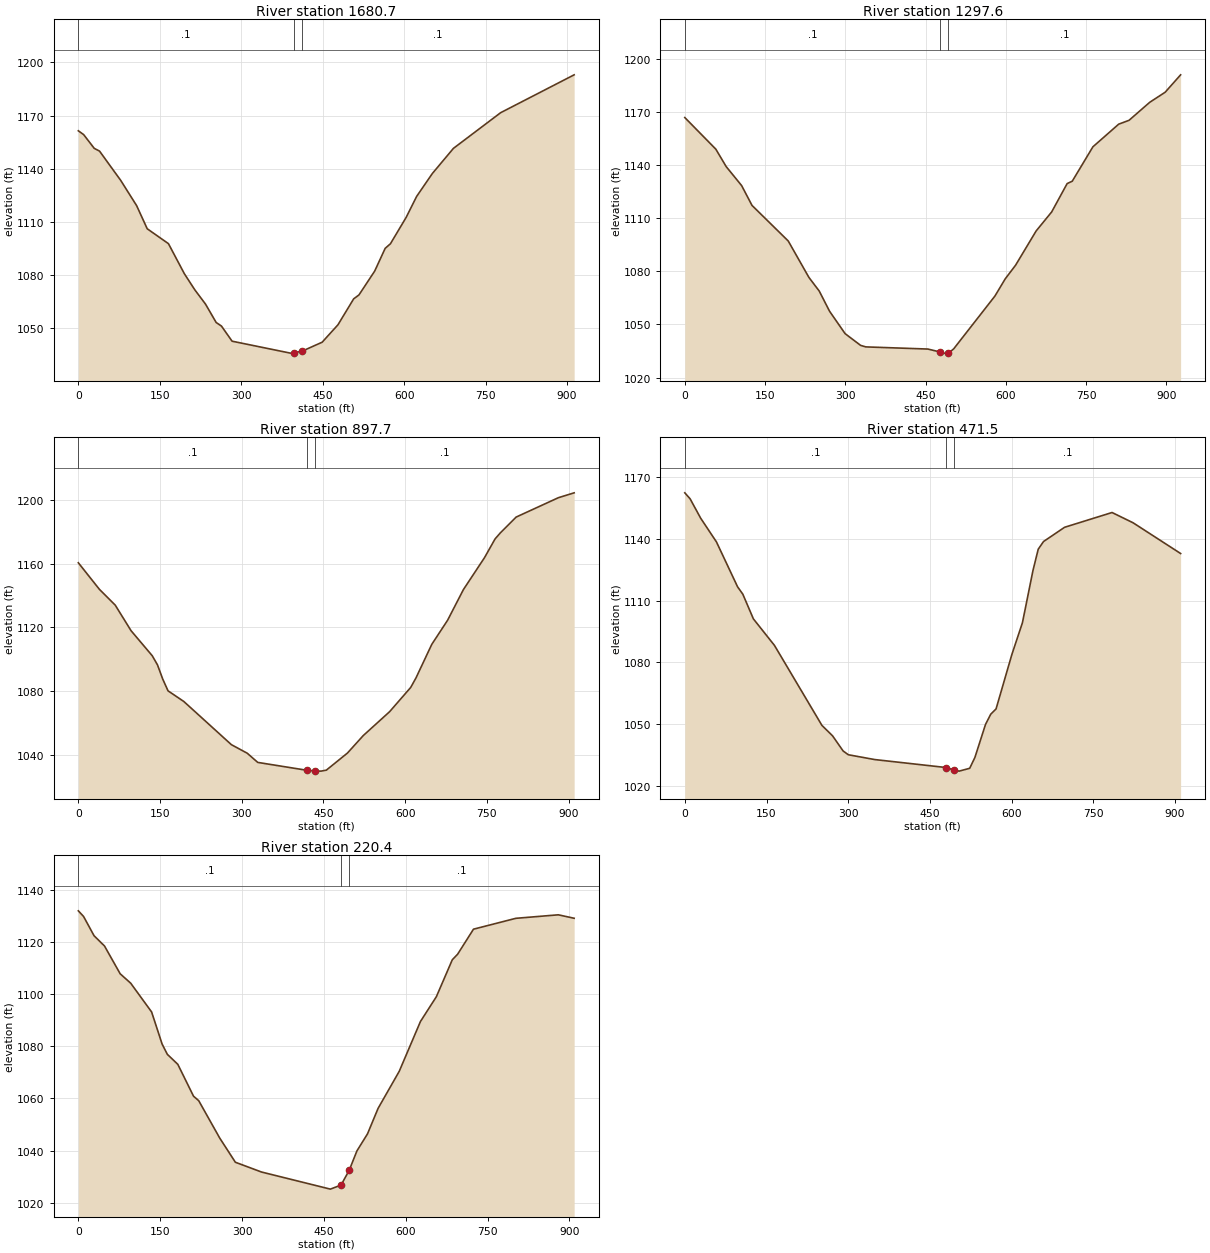
Type RM Length L Ch R = 1 ,1680.7,369.932,383.107,396.282
XS GIS Cut Line= 3
     1722334.622      404626.221     1721891.208      404507.977
     1721442.236      404438.281
#Sta/Elev= 30
       0 1161.38     9.8 1159.22    29.3 1151.48    39.1 1149.91    78.1 1133.39
   107.4 1119.16   126.9 1106.11   166.0 1097.71   195.3 1080.76   214.8 1071.56
   234.3 1063.60   253.9 1053.24   263.6 1051.24   283.2 1042.69   390.6 1035.96
   397.1 1036.15   412.1 1037.05   449.1 1042.11   478.2 1051.93   507.2 1066.58
   516.9 1068.78   545.9 1082.24   565.2 1095.06   574.9 1097.66   603.9 1112.56
   623.2 1124.38   652.2 1137.32   690.9 1151.46   777.9 1171.59   913.3 1192.95
#Mann= 3 , 0 , 0
       0     0.1       0   397.1   0.045       0   412.1     0.1       0
Bank Sta=   397.1,   412.1
Exp/Cntr=0.3,0.1

Type RM Length L Ch R = 1 ,1297.6,403.353,399.875,396.398
XS GIS Cut Line= 3
     1722392.680      404527.254     1722081.064      404196.731
     1721758.154      403851.822
#Sta/Elev= 30
       0 1166.84    58.0 1148.99    77.3 1139.17   106.3 1128.39   125.6 1117.24
   193.3 1097.16   232.0 1076.57   251.3 1068.86   270.6 1057.47   299.6 1044.84
   328.6 1038.20   338.3 1037.35   454.3 1036.13   477.8 1034.43   483.2 1033.83
   492.8 1033.83   502.5 1036.22   579.6 1066.04   598.9 1075.77   618.2 1083.45
   656.7 1102.82   685.7 1113.55   714.6 1129.55   724.2 1130.91   762.8 1150.33
   811.0 1163.11   830.3 1165.28   868.9 1175.43   897.8 1181.13   926.7 1190.96
#Mann= 3 , 0 , 0
       0     0.1       0   477.8   0.045       0   492.8     0.1       0
Bank Sta=   477.8,   492.8
Exp/Cntr=0.3,0.1

Type RM Length L Ch R = 1 ,897.7,420.697,426.213,431.728
XS GIS Cut Line= 3
     1722644.788      404141.865     1722288.349      403858.521
     1721942.338      403563.145
#Sta/Elev= 30
       0 1160.47    38.8 1143.81    67.8 1133.94    96.9 1117.91   135.6 1102.32
   145.3 1096.58   155.0 1087.63   164.7 1080.30   193.8 1073.60   281.0 1046.60
   310.0 1041.27   329.4 1035.50   419.4 1030.58   434.4 1030.16   445.6 1030.04
   455.3 1030.65   494.1 1041.36   523.1 1052.29   571.5 1067.25   610.2 1082.42
   619.9 1088.38   648.9 1109.39   678.0 1124.52   707.0 1143.70   745.7 1163.67
   765.1 1175.40   774.8 1179.19   803.8 1189.08   881.2 1201.19   910.3 1204.26
#Mann= 3 , 0 , 0
       0     0.1       0   419.4   0.045       0   434.4     0.1       0
Bank Sta=   419.4,   434.4
Exp/Cntr=0.3,0.1

Type RM Length L Ch R = 1 ,471.5,254.685,251.09,247.495
XS GIS Cut Line= 3
     1722860.119      403916.074     1722564.617      403569.826
     1722278.746      403215.891
#Sta/Elev= 30
       0 1162.37     9.7 1159.48    29.1 1150.06    58.1 1138.51    96.9 1116.68
   106.5 1113.11   125.9 1101.11   164.6 1088.21   251.8 1049.30   271.2 1044.27
   290.6 1036.90   300.2 1035.05   348.7 1032.71   479.6 1028.84   494.6 1027.64
   503.6 1027.09   523.0 1028.47   532.6 1033.77   552.0 1049.77   561.7 1054.79
   571.4 1057.33   600.4 1083.77   619.8 1099.21   639.1 1124.55   648.8 1134.97
   658.5 1138.69   697.2 1145.62   784.3 1152.80   823.0 1147.80   910.2 1132.87
#Mann= 3 , 0 , 0
       0     0.1       0   479.6   0.045       0   494.6     0.1       0
Bank Sta=   479.6,   494.6
Exp/Cntr=0.3,0.1

Type RM Length L Ch R = 1 ,220.4,234.326,220.437,206.548
XS GIS Cut Line= 3
     1723000.422      403791.237     1722842.261      403484.217
     1722423.598      403107.421
#Sta/Elev= 30
       0 1131.90     9.6 1129.74    28.8 1122.36    48.0 1118.41    76.7 1107.76
    95.9 1104.18   134.3 1093.13   153.5 1080.84   163.1 1076.89   182.3 1073.06
   211.1 1060.84   220.6 1059.13   259.0 1044.83   287.8 1035.52   335.8 1031.77
   461.9 1025.22   481.5 1026.79   496.5 1032.50   510.5 1039.86   529.9 1046.40
   549.3 1056.17   588.1 1070.40   627.0 1089.50   656.1 1098.98   685.3 1113.14
   695.0 1115.25   724.1 1124.86   801.8 1129.03   879.5 1130.37   908.6 1129.05
#Mann= 3 , 0 , 0
       0     0.1       0   481.5   0.045       0   496.5     0.1       0
Bank Sta=   481.5,   496.5
Exp/Cntr=0.3,0.1